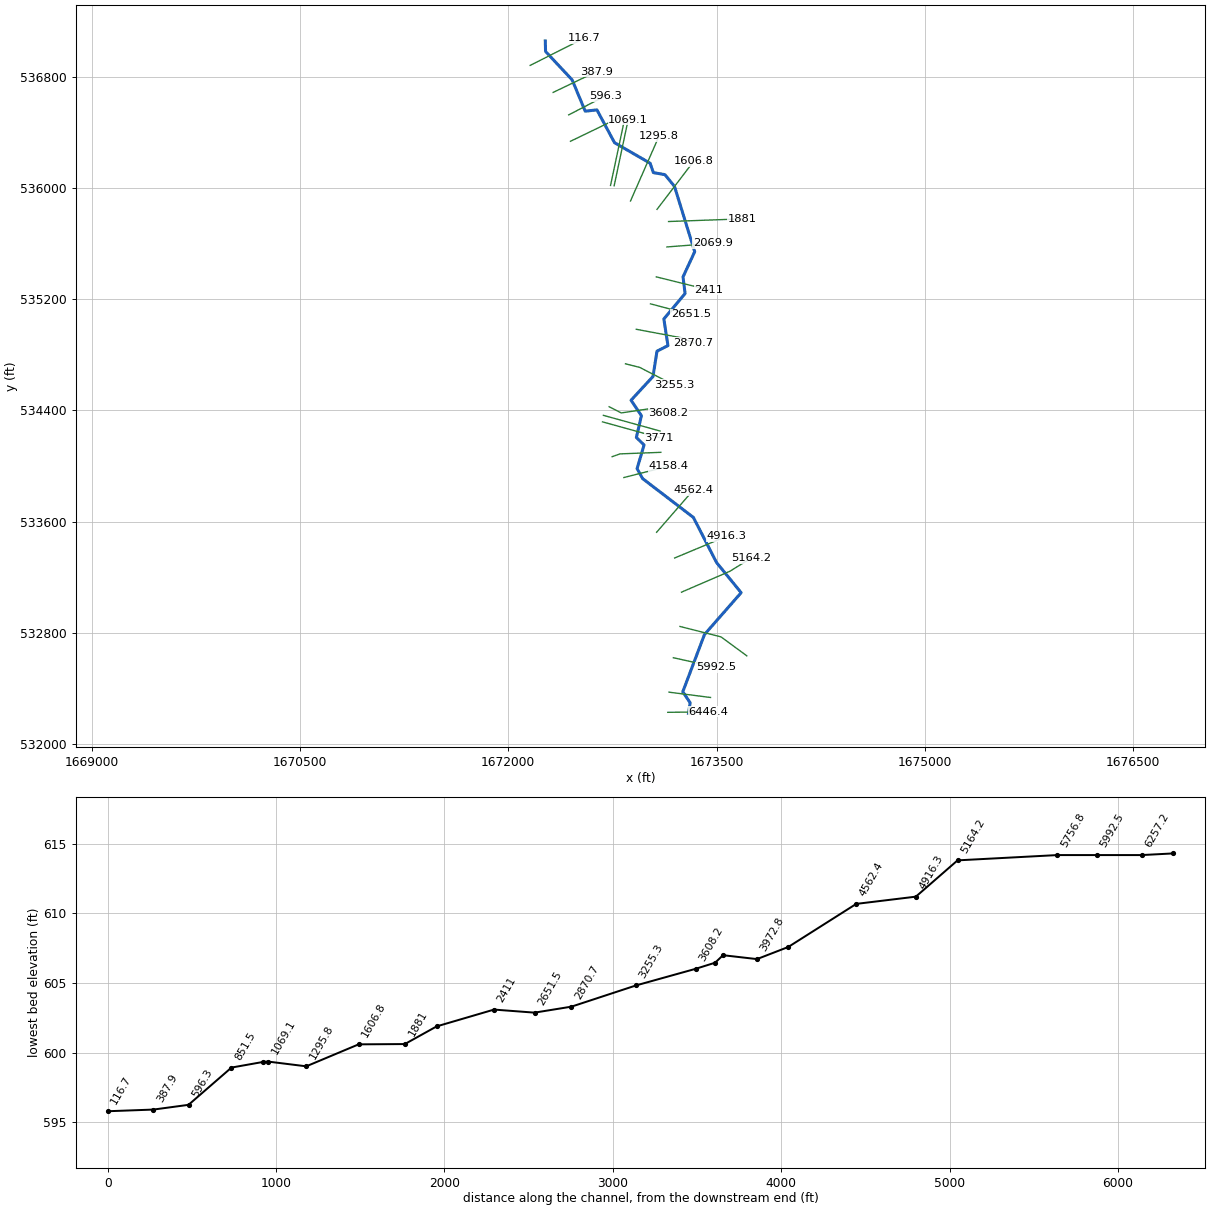
--- SleepyCr.prj (project) ---

Proj Title=SleepyCr
Current Plan=p01
Default Exp/Contr=0,0
English Units
Geom File=g01
Flow File=f01
Plan File=p01
BEGIN DESCRIPTION:
AMEC Environment & Infrastructure, 2013
Projection: NAD 1983 State Plane West Virginia South FIPS 4702 (US Feet)
Vertical Datum: NAVD 1988
END DESCRIPTION:
DSS Export Rating Curves= 0
DSS Export Rating Curve Sorted= 0
DSS Export Volume Flow Curves= 0
DXF OffsetX= 0
DXF OffsetY= 0
DXF ScaleX= 0
DXF ScaleY= 0

--- SleepyCr.p01 (plan) ---

Plan Title=Floodplain
Program Version=4.00
Geom File=g01
Flow File=f01
K Sum by GR=0
Std Step Tol=0.01
Critical Tol=0.01
Num of Std Step Trials=20
Max Error Tol=0.3
Flow Tol Ratio=0.001
Split Flow NTrial=30
Split Flow Tol=0.02
Split Flow Ratio=0.02
Log Output Level=0
Friction Slope Method=1
Unsteady Friction Slope Method=2
Unsteady Bridges Friction Slope Method=1
Global Log Level=0
CheckData=False
Run HTab=0
Run UNet=0
Run PostProcess=0
UNET Theta=0
UNET Theta Warmup=0
UNET ZTol=0
UNET ZSATol=0
UNET MxIter=0
UNET MaxInSteps=0
UNET DtIC=0
UNET DtMin=0
UNET MaxCRTS=0
UNET WFStab=0
UNET SFStab=0
UNET WFX=0
UNET SFX=0
UNET DSS MLevel=0
UNET DZMax Abort=0
UNET Convert EG Bridges=0
UNET Use Existing IB Tables=0
UNET Froude Limit=0
UNET Froude Power=0
Write IC File=0
Echo Input=False
Echo Output=False
Write Detailed=0

--- SleepyCr.f01 (steady flow) ---

Flow Title=USGS Regress. Eqn. (2010) - Western-Plateaus
Program Version=4.10
Number of Profiles= 1
Profile Names=P100yr
River Rch & RM=SleepyCr,Main            ,6446.4
    1156
River Rch & RM=SleepyCr,Main            ,5164.2
    1214
River Rch & RM=SleepyCr,Main            ,4562.4
    1224
River Rch & RM=SleepyCr,Main            ,2870.7
    1250
River Rch & RM=SleepyCr,Main            ,1069.1
    1299
River Rch & RM=SleepyCr,Main            ,596.3
    1302
Boundary for River Rch & Prof#=SleepyCr,Main            , 1
Up Type= 0
Dn Type= 3
Dn Slope=0.00068
DSS Import GetInterval= 0
DSS Import GetPeak= 0
DSS Import FillOption= 0

--- SleepyCr.g01 (geometry) ---

Geom Title=USGS 3m DEM
Program Version=4.10

River Reach=SleepyCr        ,Main
Reach XY= 30
     1673297.551      532219.428     1673309.168      532295.858
     1673256.217      532374.851     1673412.467      532787.177
     1673676.356      533088.393     1673499.272      533305.407
     1673332.606      533630.059     1672967.154      533909.573
     1672927.224      533981.622     1672977.571      534151.761
     1672922.015       534205.58     1672958.474      534362.698
     1672883.821      534473.809     1673041.807      534644.816
     1673070.453      534827.108     1673149.446      534867.038
     1673119.932      535058.879      1673272.71      535242.038
     1673257.953       535361.83     1673342.154      535543.254
     1673196.321       536013.74     1673127.744      536097.941
     1673044.411      536112.698     1673020.974      536180.407
     1672764.897      536327.976     1672638.218      536564.085
     1672553.563      536554.962     1672459.775      536780.269
     1672268.309      536984.731     1672266.302      537060.262

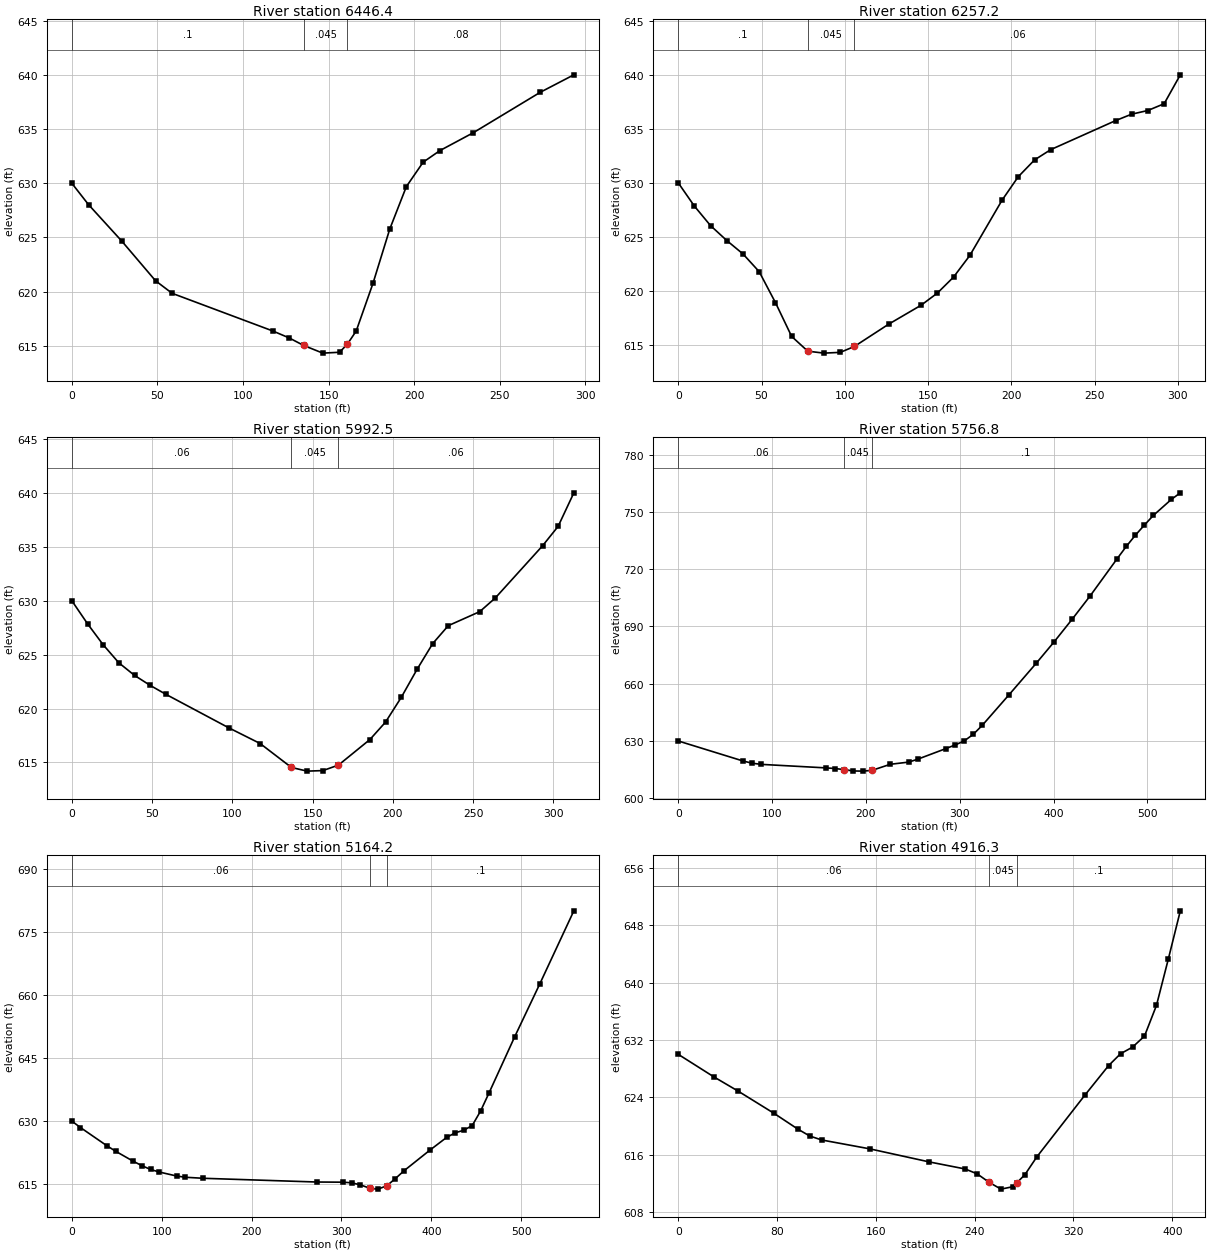
Type RM Length L Ch R = 1 ,6446.4  ,183.2,189.1,181.1
XS GIS Cut Line= 2
     1673148.392       532226.98     1673441.521      532230.262
#Sta/Elev= 20
       0     630     9.8  628.02    29.3  624.64    48.9     621    58.6  619.84
   117.3  616.37     127  615.72   135.4  615.03   146.6  614.32   156.4   614.4
  160.99  615.16   166.1  616.36   175.9  620.76   185.7  625.77   195.4  629.69
   205.2  631.94     215  633.01   234.5  634.66   273.6  638.39   293.2     640
#Mann= 3 , 0 , 0
       0      .1       0   135.4    .045       0  160.99     .08       0
Bank Sta=135.4,160.99
XS Rating Curve= 0 ,0
Exp/Cntr=0.3,0.1

Type RM Length L Ch R = 1 ,6257.2  ,266,264.8,261.7
XS GIS Cut Line= 2
     1673156.857      532372.103     1673455.937      532333.957
#Sta/Elev= 26
       0     630     9.7  627.84    19.4  626.03    29.2  624.64    38.9   623.4
    48.6  621.76    58.4  618.88    68.1  615.75    77.8  614.38    87.5   614.2
    97.3  614.27   105.8  614.82   126.4  616.89   145.9  618.65   155.6  619.77
   165.3  621.25   175.1  623.26   194.5   628.4   204.2  630.57     214  632.13
   223.7  633.08   262.6  635.77   272.3  636.37     282  636.71   291.8  637.34
   301.5  640.02
#Mann= 3 , 0 , 0
       0      .1       0    77.8    .045       0   105.8     .06       0
Bank Sta=77.8,105.8
XS Rating Curve= 0 ,0
Exp/Cntr=0.3,0.1

Type RM Length L Ch R = 1 ,5992.5  ,237.1,235.7,234.7
XS GIS Cut Line= 2
     1673188.378      532620.159     1673493.609      532552.189
#Sta/Elev= 24
       0     630     9.8  627.86    19.5  625.92    29.3  624.24    39.1  623.07
    48.9  622.14    58.6  621.32    97.7  618.22   117.3  616.76   136.8  614.54
   146.6   614.2   156.4  614.25   166.1  614.76   185.7  617.13   195.4  618.74
   205.2  621.03     215  623.62   224.8  626.02   234.5  627.68   254.1  628.98
   263.8  630.25   293.2  635.08   302.9  636.88   312.7  639.99
#Mann= 3 , 0 , 0
       0     .06       0   136.8    .045       0   166.1     .06       0
Bank Sta=136.8,166.1
XS Rating Curve= 0 ,0
Exp/Cntr=0.3,0.1

Type RM Length L Ch R = 1 ,5756.8  ,577.2,592.6,606.7
XS GIS Cut Line= 3
      1673236.23      532845.176     1673531.536      532770.167
     1673717.189      532633.726
#Sta/Elev= 30
       0     630    68.8  619.55    78.6  618.36    88.5  617.74   157.3   615.9
   167.1  615.57   176.9  614.98   186.7  614.29   196.6   614.2   206.4  614.59
   226.1  617.79   245.7  618.93   255.5   620.5     285  625.96   294.9  627.87
   304.7  629.99   314.3  633.42   323.9  638.12   352.7  654.29   381.5  670.69
   400.7  681.98   419.9  693.82   439.1  706.06   467.9  725.57   477.5  731.91
   487.1  737.74   496.7  743.04   506.3  748.13   525.5  756.53   535.1     760
#Mann= 3 , 0 , 0
       0     .06       0   176.9    .045       0   206.4      .1       0
Bank Sta=176.9,206.4
XS Rating Curve= 0 ,0
Exp/Cntr=0.3,0.1

Type RM Length L Ch R = 1 ,5164.2  ,248.1,247.8,248.1
XS GIS Cut Line= 3
     1673246.844       533092.01     1673595.297      533242.483
     1673747.507      533336.768
#Sta/Elev= 30
       0     630     9.7  628.46    38.9  624.16    48.7  622.84    68.1  620.48
    77.9  619.41    87.6   618.5    97.3  617.89   116.8  616.93   126.5  616.64
     146   616.4   272.5  615.51   301.7  615.47   311.4  615.32   321.2  614.83
   331.8  614.01   340.6  613.82   350.4   614.6   360.1  616.34   369.8  618.21
   398.4  623.08   417.2  626.14   426.7  627.22   436.1  627.82   445.5  628.93
   454.9  632.41   464.4  636.77   492.6  649.96   520.9   662.7   558.6  679.99
#Mann= 3 , 0 , 0
       0     .06       0   331.8    .045       0   350.4      .1       0
Bank Sta=331.8,350.4
XS Rating Curve= 0 ,0
Exp/Cntr=0.3,0.1

Type RM Length L Ch R = 1 ,4916.3  ,342.9,353.9,365.3
XS GIS Cut Line= 2
     1673197.637      533338.079     1673572.756      533494.786
#Sta/Elev= 25
       0     630      29  626.84    48.4  624.88    77.4  621.79    96.8  619.58
   106.5  618.61   116.2  618.06   154.9  616.83   203.3     615   232.3  614.02
     242  613.34   251.7  612.16   261.3  611.21     271  611.55   274.2   612.1
   280.7  613.23   290.4  615.72   329.1  624.28   348.5  628.44   358.1  630.08
   367.8     631   377.5  632.54   387.2  636.82   396.9  643.35   406.5     650
#Mann= 3 , 0 , 0
       0     .06       0   251.7    .045       0   274.2      .1       0
Bank Sta=251.7,274.2
XS Rating Curve= 0 ,0
Exp/Cntr=0.3,0.1

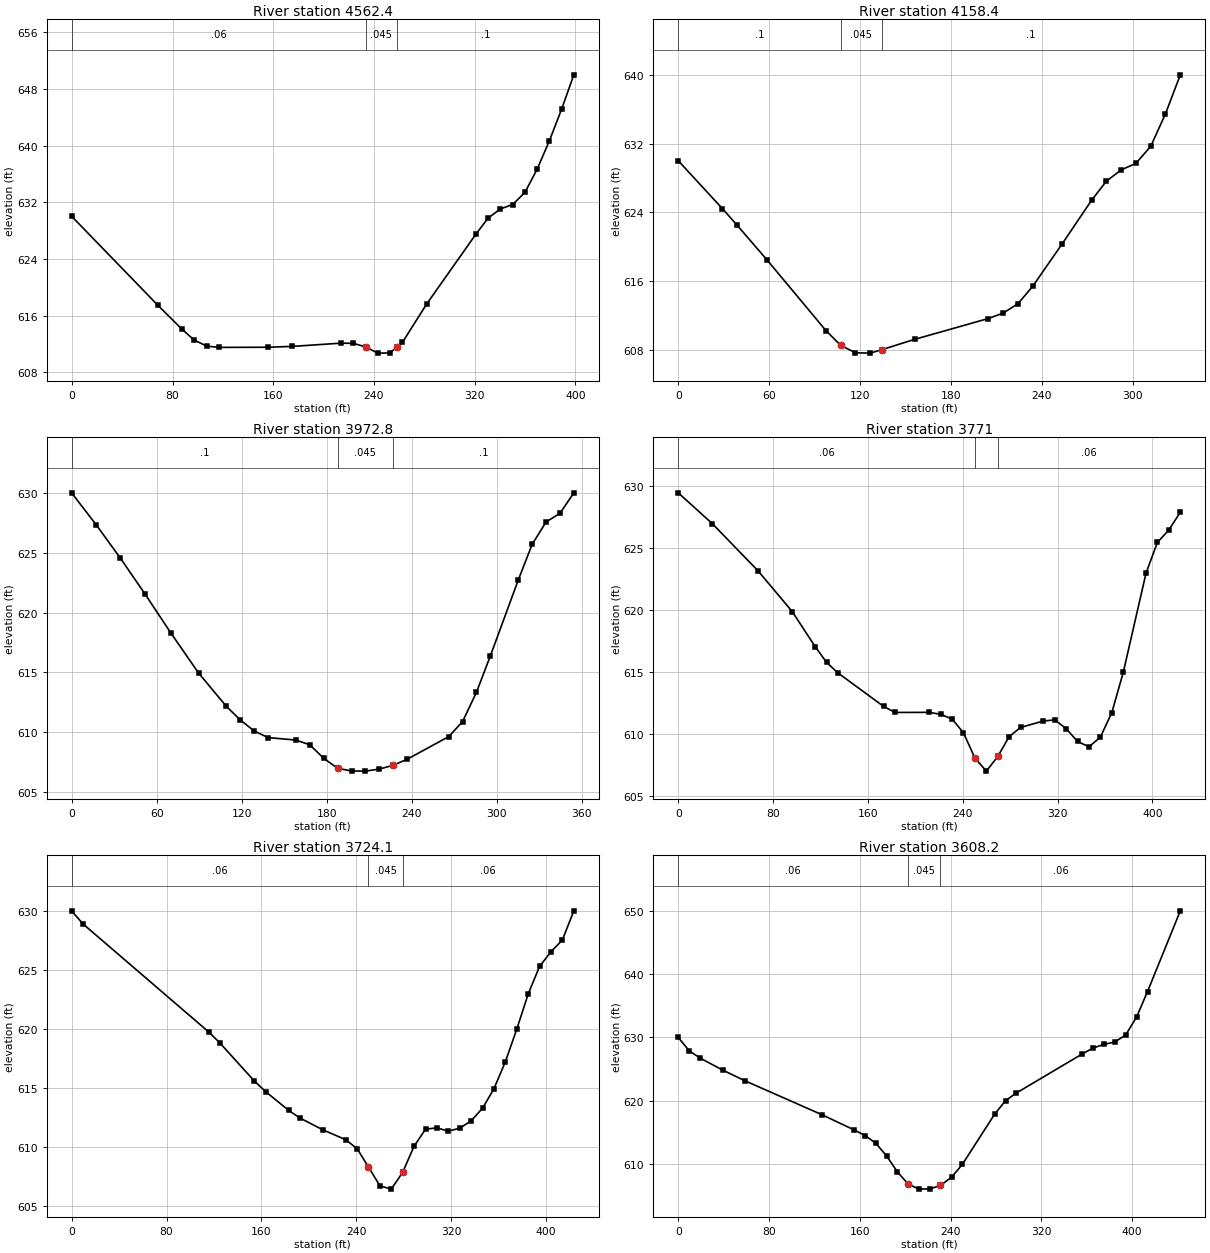
Type RM Length L Ch R = 1 ,4562.4  ,416.5,404,387.6
XS GIS Cut Line= 2
     1673067.772      533523.172      1673329.34      533824.111
#Sta/Elev= 25
       0     630    68.1   617.5    87.5  614.07    97.2  612.54     107  611.69
   116.7   611.5   155.6  611.52     175  611.64     214   612.1   223.7  612.07
   233.4  611.56   243.1  610.69   252.8  610.72   258.2  611.55   262.6  612.22
     282  617.67   320.9  627.49   330.6  629.76   340.4  631.06   350.1  631.68
   359.8  633.38   369.6  636.69   379.3  640.69     389  645.16   398.7     650
#Mann= 3 , 0 , 0
       0     .06       0   233.4    .045       0   258.2      .1       0
Bank Sta=233.4,258.2
XS Rating Curve= 0 ,0
Exp/Cntr=0.3,0.1

Type RM Length L Ch R = 1 ,4158.4  ,191.4,185.6,176.2
XS GIS Cut Line= 2
     1672831.988      533917.308     1673153.326       533998.63
#Sta/Elev= 22
       0     630    29.2  624.41      39  622.46    58.5  618.47    97.5  610.22
   107.2   608.5     117  607.63   126.7  607.59   134.4  607.99     156  609.19
   204.7  611.62   214.5  612.25   224.2  613.33     234  615.36   253.5  620.32
     273  625.41   282.7  627.62   292.5  628.93   302.2  629.69     312  631.68
   321.7  635.46   331.5     640
#Mann= 3 , 0 , 0
       0      .1       0   107.2    .045       0   134.4      .1       0
Bank Sta=107.2,134.4
XS Rating Curve= 0 ,0
Exp/Cntr=0.3,0.1

Type RM Length L Ch R = 1 ,3972.8  ,208.2,201.8,188.5
XS GIS Cut Line= 3
     1672747.979      534067.527     1672804.562      534087.692
     1673098.583      534098.788
#Sta/Elev= 28
       0     630    17.2  627.35    34.3  624.55    51.5  621.58    69.9  618.29
    89.5  614.93   109.1  612.14   118.9  611.01   128.7  610.08   138.5  609.53
   158.2  609.32     168  608.92   177.8  607.79   187.6  606.96   197.4  606.73
   207.2  606.72     217  606.89   226.8  607.21   236.6  607.71     266  609.61
   275.8  610.87   285.6  613.33   295.4  616.37   315.1  622.73   324.9  625.71
   334.7  627.58   344.5   628.3   354.3  630.02
#Mann= 3 , 0 , 0
       0      .1       0   187.6    .045       0   226.8      .1       0
Bank Sta=187.6,226.8
XS Rating Curve= 0 ,0
Exp/Cntr=0.3,0.1

Type RM Length L Ch R = 1 ,3771    ,46.9,46.9,47
XS GIS Cut Line= 2
     1672678.081      534318.257     1673086.231      534205.382
#Sta/Elev= 30
       0  629.44    28.9  626.94    67.4  623.14    96.2  619.86   115.5  617.04
   125.1  615.77   134.7  614.92   173.2  612.22   182.9  611.73   211.7  611.74
   221.4  611.58     231   611.2   240.6  610.09   250.2  608.06   259.9     607
   269.6  608.19   279.1  609.78   288.7  610.52     308  611.04   317.6  611.13
   327.2  610.43   336.8  609.39   346.5  608.96   356.1  609.75   365.7  611.71
   375.4  614.97   394.6  622.97   404.2  625.45   413.8  626.44   423.5  627.88
#Mann= 3 , 0 , 0
       0     .06       0   250.2    .045       0   269.6     .06       0
Bank Sta=250.2,269.6
XS Rating Curve= 0 ,0
Exp/Cntr=0.3,0.1

Type RM Length L Ch R = 1 ,3724.1  ,109.8,115.9,124.2
XS GIS Cut Line= 2
      1672684.59      534365.143     1673092.739      534252.269
#Sta/Elev= 30
       0  629.97     9.6  628.87   115.5  619.75   125.1   618.8     154   615.6
   163.6   614.7   182.9  613.12   192.5  612.47   211.7  611.48     231  610.64
   240.6  609.89   250.2  608.34   259.9  606.74   269.5  606.46   279.1  607.88
   288.7  610.08   298.4  611.53     308  611.64   317.6  611.36   327.2  611.61
   336.8  612.23   346.5   613.3   356.1  614.95   365.7  617.22   375.4     620
     385  622.96   394.6  625.29   404.2  626.53   413.8  627.52   423.5  629.99
#Mann= 3 , 0 , 0
       0     .06       0   250.2    .045       0   279.1     .06       0
Bank Sta=250.2,279.1
XS Rating Curve= 0 ,0
Exp/Cntr=0.3,0.1

Type RM Length L Ch R = 1 ,3608.2  ,366,352.9,338.2
XS GIS Cut Line= 4
     1672726.301      534427.083     1672813.512      534382.487
     1673001.891      534410.511      1673153.32      534382.487
#Sta/Elev= 28
       0     630     9.8  627.85    19.6   626.7    39.2  624.83    58.8  623.14
   126.5  617.79   155.1  615.37   164.6  614.49   174.1  613.27   183.7  611.24
   193.2  608.72   202.7  606.81   212.2  606.02   221.8  606.06     231   606.6
   240.8  607.89   250.3  609.92   278.9  617.89   288.4     620     298  621.22
   355.8  627.36   365.4  628.31     375  628.89   384.6  629.26   394.3  630.39
   403.9  633.23   413.5  637.24   442.4     650
#Mann= 3 , 0 , 0
       0     .06       0   202.7    .045       0     231     .06       0
Bank Sta=202.7,231
XS Rating Curve= 0 ,0
Exp/Cntr=0.3,0.1

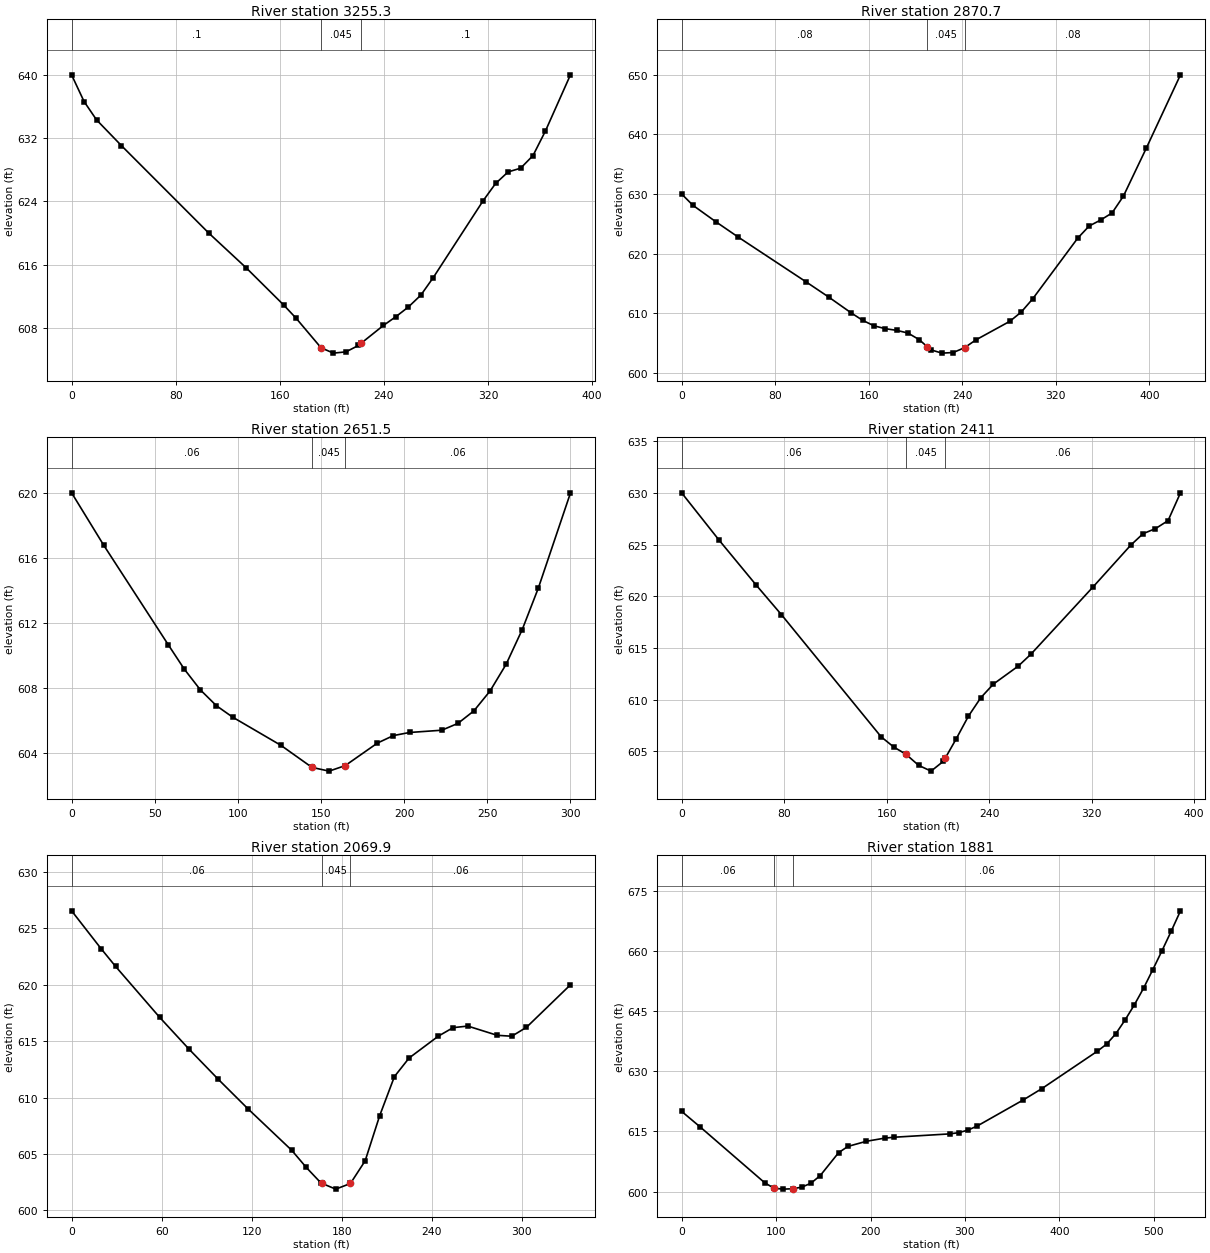
Type RM Length L Ch R = 1 ,3255.3  ,376.2,384.6,384.3
XS GIS Cut Line= 3
     1672843.687      534736.092     1672945.937      534710.391
     1673193.189      534583.627
#Sta/Elev= 25
       0  639.99     9.6  636.62    19.2   634.3    38.3  631.05   105.4     620
   134.2   615.6   162.9  610.92   172.5  609.24   191.7   605.5   201.2  604.83
   210.8  604.99   220.4   605.8   222.4  606.07   239.6  608.33   249.2  609.44
   258.7  610.65   268.3  612.15   277.9  614.38   316.2  624.09   325.8  626.27
   335.4  627.73     345   628.2   354.5  629.79   364.1  632.91   383.3     640
#Mann= 3 , 0 , 0
       0      .1       0   191.7    .045       0   222.4      .1       0
Bank Sta=191.7,222.4
XS Rating Curve= 0 ,0
Exp/Cntr=0.3,0.1

Type RM Length L Ch R = 1 ,2870.7  ,220.3,219.2,219.1
XS GIS Cut Line= 3
     1672921.351       534984.68     1673244.698      534923.825
     1673334.639      534886.352
#Sta/Elev= 29
       0     630     9.7   628.1      29  625.38    48.4  622.77   106.4  615.26
   125.8   612.7   145.2  610.02   154.8   608.8   164.5  607.88   174.2   607.4
   183.9  607.12   193.5  606.67   203.2  605.55   210.1  604.35   212.9  603.86
   222.6   603.3   232.2   603.4   241.9  604.21   251.6  605.52   280.6  608.64
   290.3  610.18     300  612.37   338.8  622.63   348.5  624.64   358.2  625.63
     368  626.82   377.7  629.64   397.2  637.66   426.5     650
#Mann= 3 , 0 , 0
       0     .08       0   210.1    .045       0   241.9     .08       0
Bank Sta=210.1,241.9
XS Rating Curve= 0 ,0
Exp/Cntr=0.3,0.1

Type RM Length L Ch R = 1 ,2651.5  ,238.8,240.4,238.6
XS GIS Cut Line= 2
     1673023.519      535167.944     1673313.671      535091.147
#Sta/Elev= 22
       0  620.01    19.4  616.77    58.1  610.66    67.8  609.15    77.5  607.87
    87.1   606.9    96.8   606.2   125.9  604.46   144.6   603.1   154.9  602.87
   164.6  603.21     184   604.6   193.6  605.06   203.3  605.25   222.7  605.39
   232.4  605.81     242  606.58   251.7   607.8   261.4  609.45   271.1  611.59
   280.8  614.15   300.1     620
#Mann= 3 , 0 , 0
       0     .06       0   144.6    .045       0   164.6     .06       0
Bank Sta=144.6,164.6
XS Rating Curve= 0 ,0
Exp/Cntr=0.3,0.1

Type RM Length L Ch R = 1 ,2411    ,331.2,341.1,345.9
XS GIS Cut Line= 2
     1673065.751      535361.932      1673443.73      535268.312
#Sta/Elev= 23
       0     630    29.2  625.43    58.4  621.05    77.9  618.22   155.8   606.4
   165.5  605.43   175.2  604.71     185  603.65   194.7  603.09   204.4  604.05
   205.8  604.35   214.2  606.18   223.9  608.41   233.6   610.2   243.4  611.51
   262.8  613.25   272.6  614.39   321.3  620.92   350.5  624.93   360.2  626.05
   369.9  626.54   379.7  627.31   389.4     630
#Mann= 3 , 0 , 0
       0     .06       0   175.2    .045       0   205.8     .06       0
Bank Sta=175.2,205.8
XS Rating Curve= 0 ,0
Exp/Cntr=0.3,0.1

Type RM Length L Ch R = 1 ,2069.9  ,192.7,188.9,187.2
XS GIS Cut Line= 2
     1673142.053      535577.427     1673473.515      535602.957
#Sta/Elev= 24
       0  626.56    19.6  623.21    29.3  621.63    58.7  617.11    78.2   614.3
    97.8  611.61   117.3  609.03   146.7  605.32   156.4   603.8   166.2  602.42
   166.8  602.39     176  601.88   185.8  602.38   195.6  604.39   205.3   608.4
   215.1  611.86   224.9  613.51   244.4  615.45   254.2   616.2     264  616.34
   283.6  615.52   293.3  615.44   303.1  616.23   332.4     620
#Mann= 3 , 0 , 0
       0     .06       0   166.8    .045       0   185.8     .06       0
Bank Sta=166.8,185.8
XS Rating Curve= 0 ,0
Exp/Cntr=0.3,0.1

Type RM Length L Ch R = 1 ,1881    ,250.6,274.2,292.8
XS GIS Cut Line= 2
     1673153.732      535760.437     1673681.598      535779.548
#Sta/Elev= 30
       0     620    19.6  616.12      88  602.19    97.8  600.84   107.6  600.61
   117.4   600.7   127.2   601.1   136.9  602.08   146.7  603.97   166.3  609.72
   176.1  611.26   195.6  612.54   215.2  613.33     225  613.55   283.7  614.38
   293.4  614.69   303.2  615.33     313  616.35   361.9  622.87   381.5  625.68
   440.2     635     450  636.77   459.7  639.34   469.5  642.77   479.3  646.53
   489.1   650.7   498.9  655.33   508.6  660.03   518.4  664.93   528.2     670
#Mann= 3 , 0 , 0
       0     .06       0    97.8    .045       0   117.4     .06       0
Bank Sta=97.8,117.4
XS Rating Curve= 0 ,0
Exp/Cntr=0.3,0.1

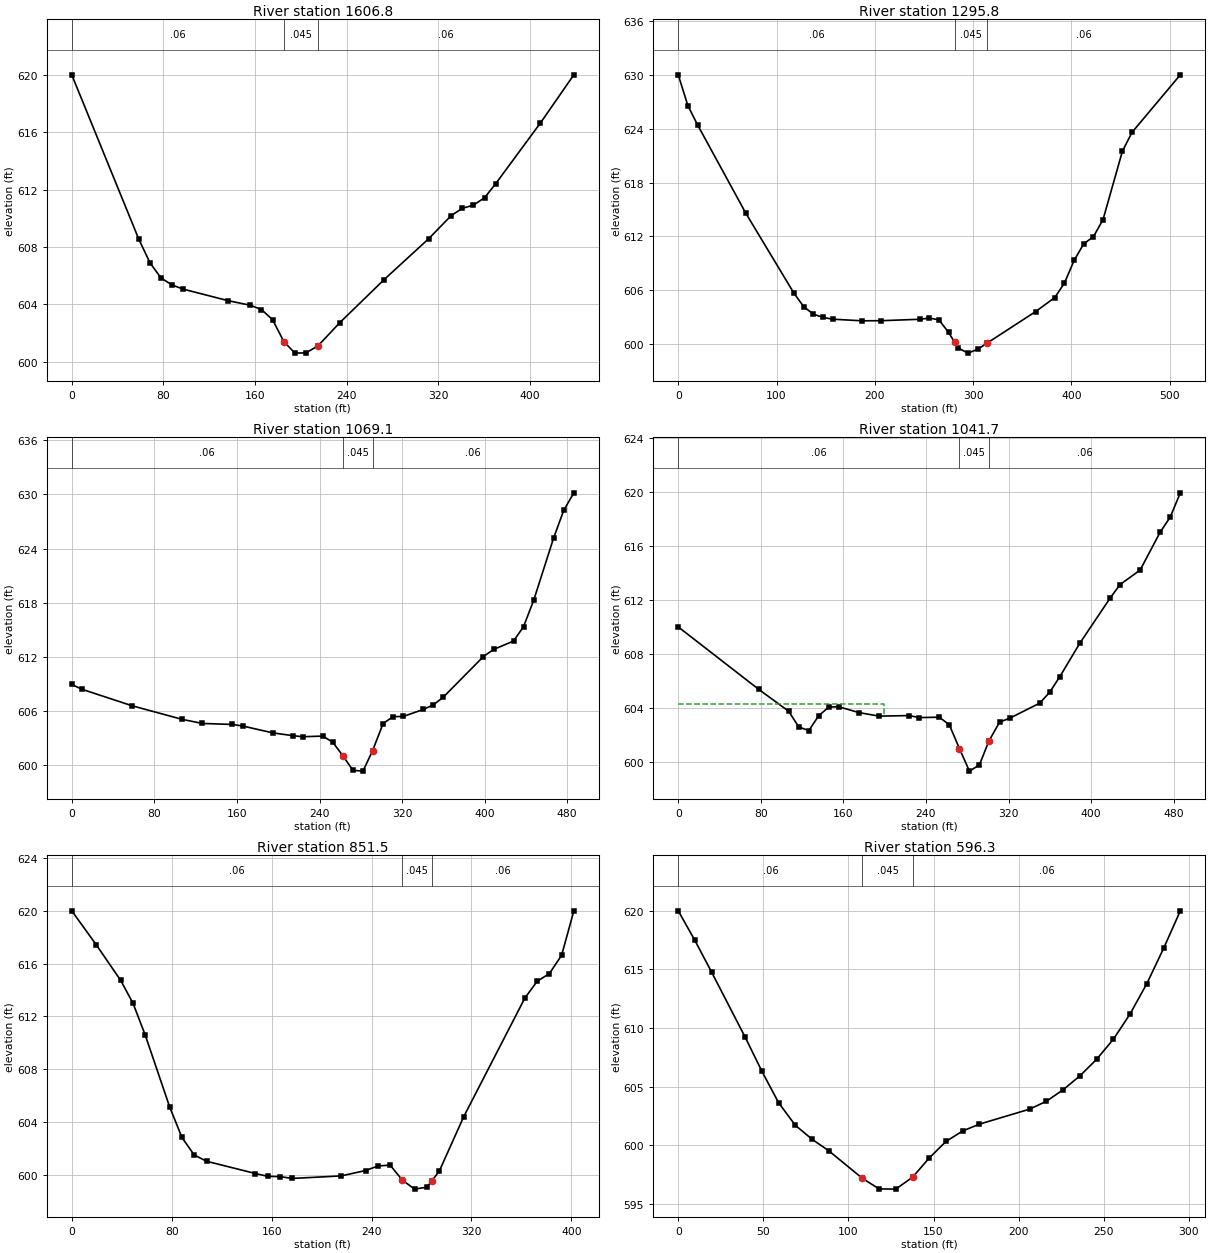
Type RM Length L Ch R = 1 ,1606.8  ,299.5,311,310.9
XS GIS Cut Line= 2
     1673070.789      535848.017     1673336.536      536196.578
#Sta/Elev= 24
       0     620    58.4  608.56    68.2   606.9    77.9  605.83    87.7  605.34
    97.4  605.05   136.4  604.25   155.8  603.93   165.6  603.63   175.3  602.92
   185.1   601.4   194.8  600.59   204.6  600.61   215.1  601.11   233.8   602.7
   272.7  605.72   311.7  608.58   331.2  610.18   340.9  610.69   350.6  610.91
   360.4  611.43   370.1  612.41   409.1  616.64   438.3     620
#Mann= 3 , 0 , 0
       0     .06       0   185.1    .045       0   215.1     .06       0
Bank Sta=185.1,215.1
XS Rating Curve= 0 ,0
Exp/Cntr=0.3,0.1

Type RM Length L Ch R = 1 ,1295.8  ,218.9,226.7,236.2
XS GIS Cut Line= 2
      1672879.73      535908.075     1673085.543      536375.584
#Sta/Elev= 30
       0     630     9.8  626.57    19.6  624.44    68.8  614.58   117.9  605.65
   127.7  604.18   137.5  603.35   147.4  602.98   157.2  602.79   186.6  602.61
   206.3  602.62   245.6  602.78   255.4  602.91   265.2  602.72     275  601.32
   281.1  600.25   284.9  599.58   294.7  599.01   304.5  599.43   314.3  600.13
   363.5  603.63   383.1   605.2   392.9  606.81   402.8  609.34   412.6  611.19
   422.4  611.97   432.2  613.89   451.9   621.5   461.7   623.6   510.8     630
#Mann= 3 , 0 , 0
       0     .06       0   281.1    .045       0   314.3     .06       0
Bank Sta=281.1,314.3
XS Rating Curve= 0 ,0
Exp/Cntr=0.3,0.1

Type RM Length L Ch R = 1 ,1069.1  ,29,27.5,26.6
XS GIS Cut Line= 2
     1672762.192      536017.763     1672863.076      536493.563
#Sta/Elev= 30
       0  608.95     9.7  608.42    58.4  606.59     107  605.08   126.5  604.63
   155.6  604.52   165.4  604.35   194.6  603.59     214  603.28   223.7  603.16
   243.2  603.23   252.9  602.55   262.6  601.06   272.4  599.44   282.1  599.35
   291.4  601.61   301.6  604.62   311.3  605.39     321   605.4   340.5  606.18
   350.2  606.68   359.9  607.54   398.8  612.04   408.6  612.82     428  613.76
   437.7  615.36   447.5  618.27   466.9   625.2   476.6  628.23   486.4  630.17
#Mann= 3 , 0 , 0
       0     .06       0   262.6    .045       0   291.4     .06       0
Bank Sta=262.6,291.4
XS Rating Curve= 0 ,0
Exp/Cntr=0.3,0.1

Type RM Length L Ch R = 1 ,1041.7  ,210.6,190.1,169
XS GIS Cut Line= 2
     1672736.144      536020.366     1672837.028      536496.166
#Sta/Elev= 30
       0     610    77.8  605.39     107  603.76   116.7   602.6   126.5  602.33
   136.2  603.44   145.9  604.07   155.6  604.09   175.1  603.66   194.6   603.4
   223.7  603.44   233.5  603.29   252.9  603.32   262.6  602.76   272.4     601
   282.1  599.33   291.8  599.79   300.8  601.53   311.3  602.96     321  603.24
   350.2  604.36   359.9  605.17   369.6  606.31   389.1   608.8   418.3  612.12
     428  613.13   447.5  614.21   466.9  617.01   476.6  618.12   486.4  619.92
#Mann= 3 , 0 , 0
       0     .06       0   272.4    .045       0   300.8     .06       0
#XS Ineff= 2 , 0
           199.3  604.29
Permanent Ineff=
       F       F
Bank Sta=272.4,300.8
XS Rating Curve= 0 ,0
Exp/Cntr=0.3,0.1

Type RM Length L Ch R = 1 ,851.5   ,253.3,255.2,254.9
XS GIS Cut Line= 2
     1672447.728      536338.162     1672809.675        536513.1
#Sta/Elev= 28
       0  619.99    19.6  617.42    39.2  614.72      49     613    58.8  610.59
    78.4  605.14    88.2  602.83      98  601.51   107.9  601.03   147.1   600.1
   156.9  599.89   166.7  599.87   176.5  599.73   215.7  599.92   235.3  600.33
   245.1  600.67   254.9  600.74   264.7   599.6   274.5  598.92   284.4  599.07
   288.4  599.56   294.2  600.27   313.8   604.4   362.8  613.39   372.6  614.65
   382.4  615.24   392.2  616.62     402  619.99
#Mann= 3 , 0 , 0
       0     .06       0   264.7    .045       0   288.4     .06       0
Bank Sta=264.7,288.4
XS Rating Curve= 0 ,0
Exp/Cntr=0.3,0.1

Type RM Length L Ch R = 1 ,596.3   ,210.6,208.4,206.2
XS GIS Cut Line= 2
     1672434.788      536528.152     1672696.774      536663.775
#Sta/Elev= 27
       0     620     9.8  617.47    19.7  614.74    39.3  609.22    49.2  606.29
      59  603.61    68.8  601.69    78.7  600.49    88.5  599.51   108.2  597.16
     118  596.26   127.8  596.24   137.7  597.26   147.5   598.9   157.3  600.31
   167.2  601.21     177  601.79   206.5  603.07   216.3  603.74   226.2  604.73
     236  605.91   245.8  607.32   255.7  609.04   265.5   611.2   275.3  613.78
   285.2   616.8     295     620
#Mann= 3 , 0 , 0
       0     .06       0   108.2    .045       0   137.7     .06       0
Bank Sta=108.2,137.7
XS Rating Curve= 0 ,0
Exp/Cntr=0.3,0.1

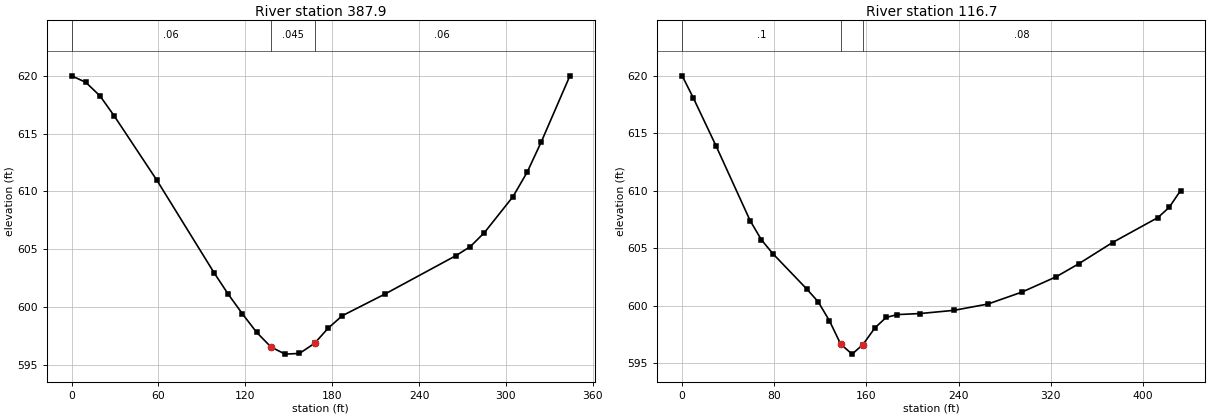
Type RM Length L Ch R = 1 ,387.9   ,270.9,271.2,271.3
XS GIS Cut Line= 2
     1672322.759      536689.939     1672633.211      536838.604
#Sta/Elev= 23
       0     620     9.8  619.44    19.7  618.25    29.5  616.52      59  610.94
    98.4  602.95   108.2  601.09     118  599.39   127.8  597.79   137.7  596.52
   147.5   595.9   157.4  595.96   167.9  596.84     177  598.12   186.9  599.22
   216.4   601.1   265.5  604.43   275.4  605.21   285.2  606.43   304.9  609.54
   314.7  611.66   324.5   614.3   344.2     620
#Mann= 3 , 0 , 0
       0     .06       0   137.7    .045       0   167.9     .06       0
Bank Sta=137.7,167.9
XS Rating Curve= 0 ,0
Exp/Cntr=0.3,0.1

Type RM Length L Ch R = 1 ,116.7   ,131.4,116.7,102
XS GIS Cut Line= 2
     1672157.598      536884.644     1672543.937      537079.332
#Sta/Elev= 25
       0  619.99     9.8  618.04    29.5  613.87      59  607.39    68.8  605.72
    78.7  604.52   108.2  601.44     118  600.34   127.8  598.69   137.6  596.65
   147.5  595.78   156.9  596.61   167.2  598.05     177  598.97   186.8  599.22
   206.5  599.31     236  599.59   265.5  600.14     295  601.18   324.5   602.5
   344.1  603.63   373.6  605.49     413  607.66   422.8  608.55   432.6     610
#Mann= 3 , 0 , 0
       0      .1       0   137.6    .045       0   156.9     .08       0
Bank Sta=137.6,156.9
XS Rating Curve= 0 ,0
Exp/Cntr=0.3,0.1

Chan Stop Cuts=-1
Use User Specified Reach Order=0
Composite Channel Slope=5